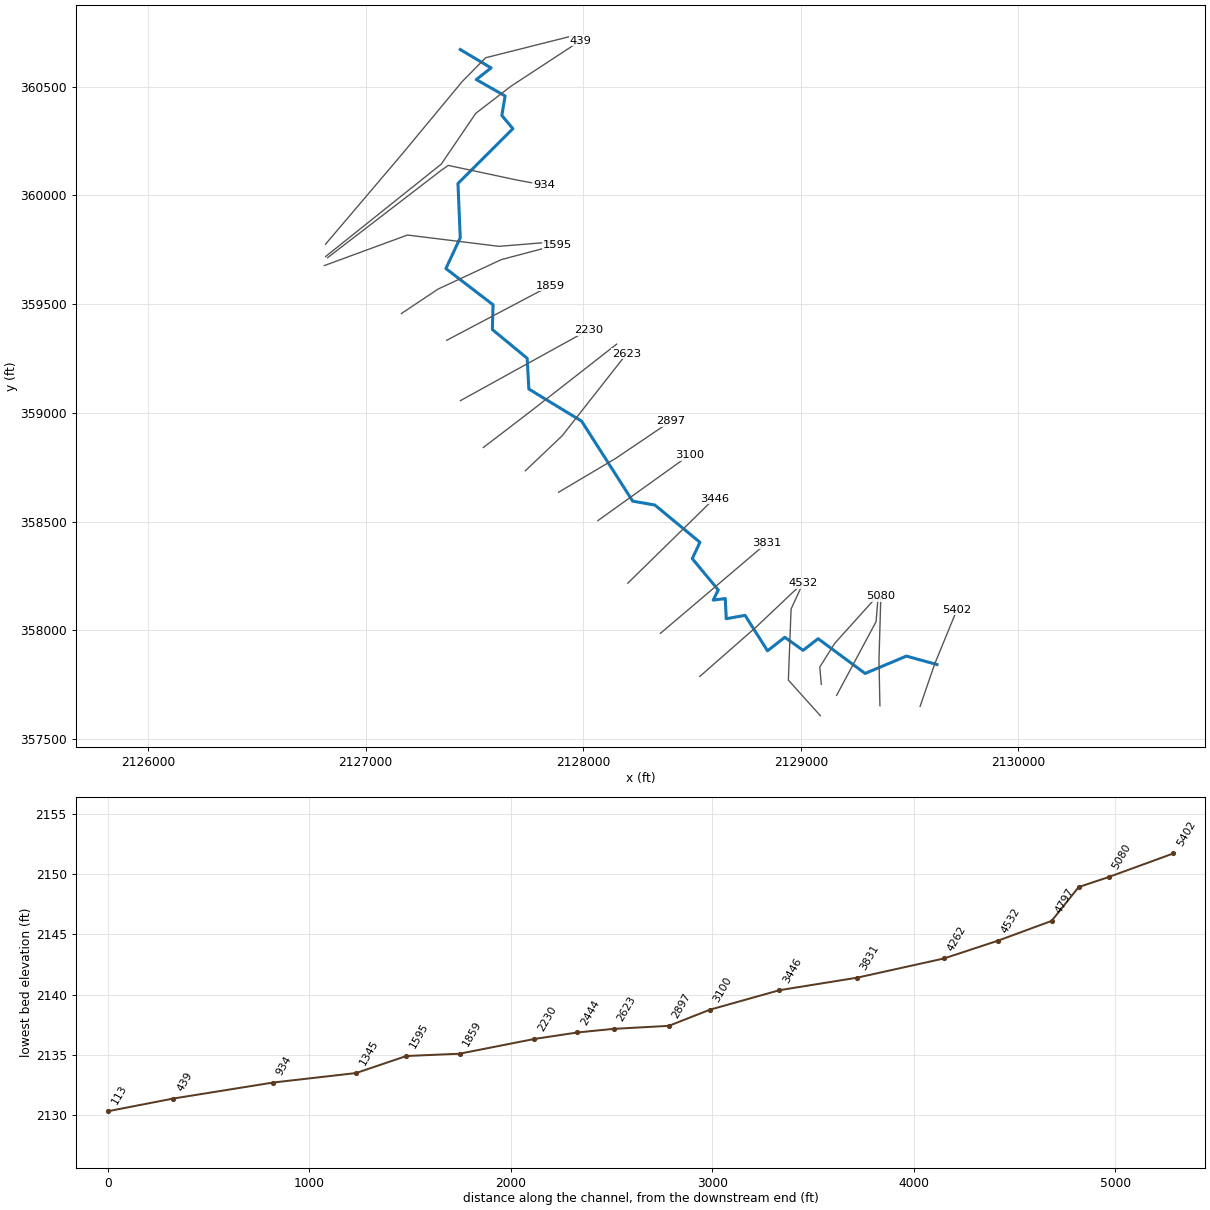
--- CLBRSNCKT2.prj (project) ---

Proj Title=CLBRSNCKT2
Current Plan=p01
Default Exp/Contr=0.3,0.1
English Units
Geom File=g01
Flow File=f01
Plan File=p01
Y Axis Title=Elevation
X Axis Title(PF)=Main Channel Distance
X Axis Title(XS)=Station
BEGIN DESCRIPTION:
Stream Name- Cuberson Creek Tributary 2
Flood Zone: Zone A
Greenbrier County, WV
County-Wide Study
WVDHSEM-2018-3, Flood Risk Project
HEC-RAS Version: 5.0.7
General Notes:
For the Hydrology regression was used.
END DESCRIPTION:
DSS Export Rating Curves= 0
DSS Export Rating Curve Sorted= 0
DSS Export Volume Flow Curves= 0
DXF Filename=CLBRSNCKT2.G2.
DXF OffsetX= 0
DXF OffsetY= 0
DXF ScaleX= 1
DXF ScaleY= 10

--- CLBRSNCKT2.p01 (plan) ---

Plan Title=Floodplain
Program Version=5.07
Short Identifier=Floodplain
Geom File=g01
Flow File=f01
Subcritical Flow
K Sum by GR= 0
Std Step Tol= 0.01
Critical Tol= 0.01
Num of Std Step Trials= 20
Max Error Tol= 0.3
Flow Tol Ratio= 0.001
Split Flow NTrial= 30
Split Flow Tol= 0.02
Split Flow Ratio= 0.02
Log Output Level= 0
Friction Slope Method= 1
Unsteady Friction Slope Method= 2
Unsteady Bridges Friction Slope Method= 1
Parabolic Critical Depth
Global Vel Dist= 0 , 0 , 0
Global Log Level= 0
CheckData=True
Encroach Param=-1 ,0,0, 0
Computation Interval=1MIN
Output Interval=1HOUR
Instantaneous Interval=1HOUR
Mapping Interval=1HOUR
Computation Time Step Use Courant=        0
Computation Time Step Use Time Series=    0
Computation Time Step Count To Double=0
Computation Time Step Max Doubling=0
Computation Time Step Max Halving=0
Computation Time Step Residence Courant=0
Run HTab= 0
Run UNet= 0
Run Sediment= 0
Run PostProcess= 0
Run WQNet= 0
Run RASMapper= 0
UNET Theta= 1
UNET Theta Warmup= 1
UNET ZTol= 0.02
UNET ZSATol= 0.02
UNET MxIter= 20
UNET Max Iter WO Improvement= 0
UNET MaxInSteps= 0
UNET DtIC= 0
UNET DtMin= 0
UNET MaxCRTS= 20
UNET WFStab= 2
UNET SFStab= 1
UNET WFX= 1
UNET SFX= 1
UNET 1D Methodology=Finite Difference
UNET DSS MLevel= 4
UNET Pardiso=0
UNET DZMax Abort= 100
UNET Use Existing IB Tables=-1
UNET Froude Reduction=False
UNET Froude Limit= 0.8
UNET Froude Power= 4
UNET D1 Cores= 0
UNET D2 Coriolis=0
UNET D2 Cores= 0
UNET D2 Theta= 1
UNET D2 Theta Warmup= 1
UNET D2 Z Tol= 0.01
UNET D2 Volume Tol= 0.01
UNET D2 Max Iterations= 20
UNET D2 Equation= 0
UNET D2 RampUpFraction=0.1
UNET D2 TimeSlices= 1
UNET D2 BCVolumeCheck=0
UNET D1D2 MaxIter= 0
UNET D1D2 ZTol=0.01
UNET D1D2 QTol=0.1
UNET D1D2 MinQTol=1
Write IC File= 0
Write IC File at Fixed DateTime=0
Write IC File at Sim End=0
Echo Input=False
Echo Parameters=False
Echo Output=False
Write Detailed= 0
HDF Write Warmup=0
HDF Write Time Slices=0
HDF Flush=0
HDF Face Node Velocities=0
HDF Compression= 1
HDF Chunk Size= 1
HDF Spatial Parts= 1
HDF Use Max Rows=0
HDF Fixed Rows= 1
Calibration Method= 0
Calibration Iterations= 20
Calibration Max Change=0.05
Calibration Tolerance=0.2
Calibration Maximum=1.5
Calibration Minimum=0.5
Calibration Optimization Method= 1
WQ AD Non Conservative
WQ ULTIMATE=-1
WQ Max Comp Step=1HOUR
WQ Output Interval=15MIN
WQ Output Selected Increments= 0
WQ Output face flow=0
WQ Output face velocity=0
WQ Output face area=0
WQ Output face dispersion=0
WQ Output cell volume=0
WQ Output cell surface area=0
WQ Output cell continuity=0
WQ Output cumulative cell continuity=0
WQ Output face conc=0
WQ Output face dconc_dx=0
WQ Output face courant=0
WQ Output face peclet=0
WQ Output face adv mass=0
WQ Output face disp mass=0
WQ Output cell mass=0
WQ Output cell source sink temp=0
WQ Output nsm pathways=0
WQ Output nsm derived pathways=0
WQ Output MaxMinRange=-1
WQ Daily Max Min Mean=-1
WQ Daily Range=0
WQ Daily Time=0
WQ Create Restart=0
WQ Fixed Restart=0
WQ System Summary=0
WQ Write To DSS=0
WQ Use Fixed Temperature=0
Sorting and Armoring Iterations= 10
XS Update Threshold= 0.02
Bed Roughness Predictor= 0
Hydraulics Update Threshold= 0.02
Energy Slope Method= 1
Volume Change Method= 1
Sediment Retention Method= 0
XS Weighting Method= 0
Number of US Weighted Cross Sections= 1
Number of DS Weighted Cross Sections= 1
Upstream XS Weight=0
Main XS Weight=1
Downstream XS Weight=0
Number of DS XS's Weighted with US Boundary= 1
Upstream Boundary Weight= 1
Weight of XSs Associated with US Boundary= 0
Number of US XS's Weighted with DS Boundary= 1
Downstream Boundary Weight= 0.5
Weight of XSs Associated with DS Boundary= 0.5
Percentile Method= 0
Sediment Output Level= 3
Mass or Volume Output= 0
Output Increment Type= 1
Profile and TS Output Increment= 1
XS Output Flag= 0
XS Output Increment= 10
Write Gradation File= 0
Read Gradation Hotstart= 0
Write HDF5 File= 1
Write Binary Output= 1
Write DSS Sediment File= 0
SV Curve= 0
Specific Gage Flag= 0

--- CLBRSNCKT2.f01 (steady flow) ---

Flow Title=Flow
Program Version=5.07
Number of Profiles= 6
Profile Names=f1p,f10p,f4p,f2p,f02p,f1pplus
River Rch & RM=CLBRSNCKT2,Main            ,5402
     223     114     154     187     317     330
River Rch & RM=CLBRSNCKT2,Main            ,3831
     483     253     338     408     676     714
Boundary for River Rch & Prof#=BURNSRN,Main            , 1
Up Type= 0
Dn Type= 3
Dn Slope=0.0012
Boundary for River Rch & Prof#=BURNSRN,Main            , 2
Up Type= 0
Dn Type= 3
Dn Slope=0.0012
Boundary for River Rch & Prof#=BURNSRN,Main            , 3
Up Type= 0
Dn Type= 3
Dn Slope=0.0012
Boundary for River Rch & Prof#=BURNSRN,Main            , 4
Up Type= 0
Dn Type= 3
Dn Slope=0.0012
Boundary for River Rch & Prof#=BURNSRN,Main            , 5
Up Type= 0
Dn Type= 3
Dn Slope=0.0012
Boundary for River Rch & Prof#=BURNSRN,Main            , 6
Up Type= 0
Dn Type= 3
Dn Slope=0.0012
Boundary for River Rch & Prof#=BURNSRNT1,Main            , 1
Up Type= 0
Dn Type= 3
Dn Slope=0.00496
Boundary for River Rch & Prof#=BURNSRNT1,Main            , 2
Up Type= 0
Dn Type= 3
Dn Slope=0.00496
Boundary for River Rch & Prof#=BURNSRNT1,Main            , 3
Up Type= 0
Dn Type= 3
Dn Slope=0.00496
Boundary for River Rch & Prof#=BURNSRNT1,Main            , 4
Up Type= 0
Dn Type= 3
Dn Slope=0.00496
Boundary for River Rch & Prof#=BURNSRNT1,Main            , 5
Up Type= 0
Dn Type= 3
Dn Slope=0.00496
Boundary for River Rch & Prof#=BURNSRNT1,Main            , 6
Up Type= 0
Dn Type= 3
Dn Slope=0.00496
Boundary for River Rch & Prof#=CLBRSNCKT1,Main            , 1
Up Type= 0
Dn Type= 3
Dn Slope=0.00848
Boundary for River Rch & Prof#=CLBRSNCKT1,Main            , 2
Up Type= 0
Dn Type= 3
Dn Slope=0.00848
Boundary for River Rch & Prof#=CLBRSNCKT1,Main            , 3
Up Type= 0
Dn Type= 3
Dn Slope=0.00848
Boundary for River Rch & Prof#=CLBRSNCKT1,Main            , 4
Up Type= 0
Dn Type= 3
Dn Slope=0.00848
Boundary for River Rch & Prof#=CLBRSNCKT1,Main            , 5
Up Type= 0
Dn Type= 3
Dn Slope=0.00848
Boundary for River Rch & Prof#=CLBRSNCKT1,Main            , 6
Up Type= 0
Dn Type= 3
Dn Slope=0.00848
Boundary for River Rch & Prof#=CLBRSNCKT2,Main            , 1
Up Type= 0
Dn Type= 3
Dn Slope=0.00274
Boundary for River Rch & Prof#=CLBRSNCKT2,Main            , 2
Up Type= 0
Dn Type= 3
Dn Slope=0.00274
Boundary for River Rch & Prof#=CLBRSNCKT2,Main            , 3
Up Type= 0
Dn Type= 3
Dn Slope=0.00274
Boundary for River Rch & Prof#=CLBRSNCKT2,Main            , 4
Up Type= 0
Dn Type= 3
Dn Slope=0.00274
Boundary for River Rch & Prof#=CLBRSNCKT2,Main            , 5
Up Type= 0
Dn Type= 3
Dn Slope=0.00274
Boundary for River Rch & Prof#=CLBRSNCKT2,Main            , 6
Up Type= 0
Dn Type= 3
Dn Slope=0.00274
Boundary for River Rch & Prof#=INDIANCK,Main            , 1
Up Type= 0
Dn Type= 3
Dn Slope=0.00176
Boundary for River Rch & Prof#=INDIANCK,Main            , 2
Up Type= 0
Dn Type= 3
Dn Slope=0.00176
Boundary for River Rch & Prof#=INDIANCK,Main            , 3
Up Type= 0
Dn Type= 3
Dn Slope=0.00176
Boundary for River Rch & Prof#=INDIANCK,Main            , 4
Up Type= 0
Dn Type= 3
Dn Slope=0.00176
Boundary for River Rch & Prof#=INDIANCK,Main            , 5
Up Type= 0
Dn Type= 3
Dn Slope=0.00176
Boundary for River Rch & Prof#=INDIANCK,Main            , 6
Up Type= 0
Dn Type= 3
Dn Slope=0.00176
Boundary for River Rch & Prof#=LTROARCK,Main            , 1
Up Type= 0
Dn Type= 3
Dn Slope=0.04436
Boundary for River Rch & Prof#=LTROARCK,Main            , 2
Up Type= 0
Dn Type= 3
Dn Slope=0.04436
Boundary for River Rch & Prof#=LTROARCK,Main            , 3
Up Type= 0
Dn Type= 3
Dn Slope=0.04436
Boundary for River Rch & Prof#=LTROARCK,Main            , 4
Up Type= 0
Dn Type= 3
Dn Slope=0.04436
Boundary for River Rch & Prof#=LTROARCK,Main            , 5
Up Type= 0
Dn Type= 3
Dn Slope=0.04436
Boundary for River Rch & Prof#=LTROARCK,Main            , 6
Up Type= 0
Dn Type= 3
Dn Slope=0.04436
Boundary for River Rch & Prof#=MLGNCKTR5,Main            , 1
Up Type= 0
Dn Type= 3
Dn Slope=0.0247
Boundary for River Rch & Prof#=MLGNCKTR5,Main            , 2
Up Type= 0
Dn Type= 3
Dn Slope=0.0247
Boundary for River Rch & Prof#=MLGNCKTR5,Main            , 3
Up Type= 0
Dn Type= 3
Dn Slope=0.0247
Boundary for River Rch & Prof#=MLGNCKTR5,Main            , 4
Up Type= 0
Dn Type= 3
Dn Slope=0.0247
Boundary for River Rch & Prof#=MLGNCKTR5,Main            , 5
Up Type= 0
Dn Type= 3
Dn Slope=0.0247
Boundary for River Rch & Prof#=MLGNCKTR5,Main            , 6
Up Type= 0
Dn Type= 3
Dn Slope=0.0247
Boundary for River Rch & Prof#=ROARINGCK,Main            , 1
Up Type= 0
Dn Type= 3
Dn Slope=0.01435
Boundary for River Rch & Prof#=ROARINGCK,Main            , 2
Up Type= 0
Dn Type= 3
Dn Slope=0.01435
Boundary for River Rch & Prof#=ROARINGCK,Main            , 3
Up Type= 0
Dn Type= 3
Dn Slope=0.01435
Boundary for River Rch & Prof#=ROARINGCK,Main            , 4
Up Type= 0
Dn Type= 3
Dn Slope=0.01435
Boundary for River Rch & Prof#=ROARINGCK,Main            , 5
Up Type= 0
Dn Type= 3
Dn Slope=0.01435
Boundary for River Rch & Prof#=ROARINGCK,Main            , 6
Up Type= 0
Dn Type= 3
Dn Slope=0.01435
DSS Import GetInterval= 0
DSS Import GetPeak= 0
DSS Import FillOption= 0

--- CLBRSNCKT2.g01 (geometry) ---

Geom Title=Geometry
Program Version=5.07

River Reach=CLBRSNCKT2      ,Main
Reach XY= 30
2129625.76438797357843.0579588712129485.21512836357881.940427035
2129295.38873637357802.1718857882129079.55517855357961.894335359
2129010.38865021357908.5607806152128926.22182378 357968.28310211
2128846.77742887357906.3386722062128743.72186071 358069.11656186
2128657.05536738358053.8387052862128652.61082247358146.338520288
 2128597.0551593358139.3943084482128620.66633254358185.782995194
2128500.94413105358329.9497016222128536.22194764358404.949879706
2128328.99992111358576.3386445342128227.05524313358594.116496116
2127992.33294353358961.8943038582127749.83310047359109.394336954
2127742.24500503359250.6930122472127582.05522078359383.005338281
2127585.38854745359496.6163315332127368.44409946359663.282992944
 2127434.5551877359804.9497043642127423.99976262360054.394087359
2127676.49991378360306.0609068722127625.66635403360366.894118533
2127640.66632405360456.6163800362127508.16658905 360531.89411661
2127576.22189912360585.5052298612127434.56240556360669.921727702

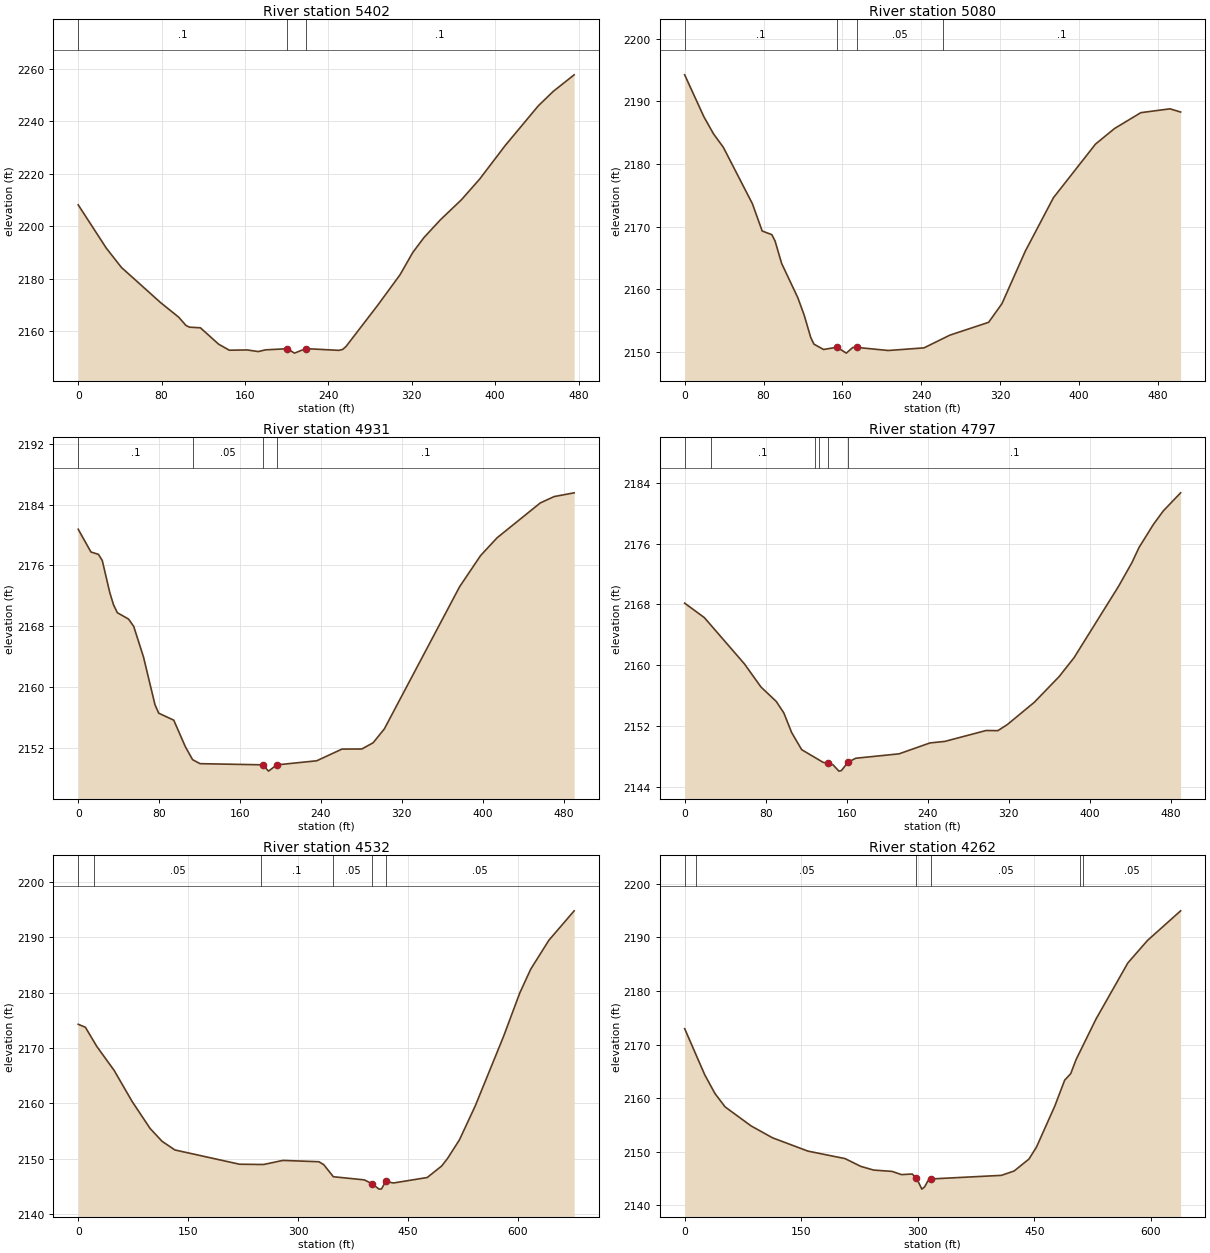
Type RM Length L Ch R = 1 ,5402    ,312,321.7,318.2
XS GIS Cut Line= 3
2129548.16677412357650.9425294552129615.54393595357846.762019694
2129717.61098903358095.386850536
#Sta/Elev= 30
       0 2208.19      27 2191.68    41.5 2184.35    79.1 2170.96    96.4 2165.44
   103.4 2162.28   106.8 2161.63   117.2  2161.4   134.8 2155.13     145 2152.86
   162.3 2152.96   172.7 2152.34   179.7    2153  200.622153.424   207.5 2151.75
  218.37 2153.46     250 2152.81   253.6 2153.13   256.9 2154.26   287.4 2170.01
   308.7 2181.55   320.9 2190.01   331.6 2195.69   347.5 2202.51   367.7 2210.14
   385.3 2218.07   409.6 2230.74   441.5 2245.92   455.8  2251.4   475.8 2257.68
#Mann= 3 ,-1 , 0
       0      .1       0  200.62    .045       0  218.37      .1       0
Bank Sta=200.62,218.37
XS Rating Curve= 0 ,0
Exp/Cntr=0.3,0.1

Type RM Length L Ch R = 1 ,5080    ,151.5,148.5,140.8
XS GIS Cut Line= 3
2129363.44437453357653.7200829542129359.16190279357862.794139862
2129367.61103287358156.497948781
#Sta/Elev= 30
       0 2194.22    19.5 2187.52    29.3 2184.78    39.2 2182.65    68.7 2173.63
    78.6 2169.28    88.4  2168.7    91.7 2167.67    98.3 2164.11   114.7 2158.64
   121.2 2155.84   127.8 2152.29   131.1 2151.21   140.9 2150.36   154.42150.728
   163.9 2149.78   170.5 2150.69  174.412150.696   206.5  2150.2   242.7 2150.62
   268.9 2152.65   308.2  2154.7   321.7 2157.67   345.3 2166.03   373.9 2174.59
   416.6 2183.16     436 2185.66   462.6 2188.18   492.1 2188.79   502.9 2188.28
#Mann= 4 ,-1 , 0
       0      .1       0   154.4    .045       0  174.41     .05       0
  262.08      .1       0
Bank Sta=154.4,174.41
XS Rating Curve= 0 ,0
Exp/Cntr=0.3,0.1

Type RM Length L Ch R = 1 ,4931    ,137.5,134.4,134.4
XS GIS Cut Line= 3
2129164.47402743357701.4722531272129345.88293675358040.468699826
2129354.43419847358146.137862491
#Sta/Elev= 30
       0 2180.75    12.6 2177.76      20 2177.45    23.8 2176.64    31.2 2172.44
    34.9 2170.83    38.7 2169.78    49.8 2168.94    54.9 2167.98    64.6 2163.94
    75.9  2157.7    79.6 2156.57    94.5 2155.65     106 2152.15   113.1 2150.46
   120.5 2149.93   182.5 2149.78   188.2 2148.95   196.4 2149.77   235.9 2150.31
   260.9 2151.85   280.5 2151.86   291.7 2152.68   302.8 2154.51   377.2 2173.19
   397.9 2177.28   414.3 2179.63   457.1 2184.22   470.8 2185.05   490.5 2185.54
#Mann= 4 ,-1 , 0
       0      .1       0   113.1     .05       0   182.5    .045       0
   196.4      .1       0
Bank Sta=182.5,196.4
XS Rating Curve= 0 ,0
Exp/Cntr(USF)=0,0
Exp/Cntr=0.3,0.1

Type RM Length L Ch R = 1 ,4797    ,247.3,265,263.3
XS GIS Cut Line= 4
2129094.00003153 357752.331434282129087.05549163357831.497942612
2129155.11112979357939.831387371 2129344.0001877358149.553408861
#Sta/Elev= 30
       0 2168.17    19.4 2166.28    58.9 2160.22    75.4 2157.16    90.4 2155.28
    97.9 2153.77   105.6  2151.2   115.5 2148.95   136.6 2147.29   141.82147.156
   146.4 2146.97   152.3 2146.13   154.7  2146.2  161.48 2147.32   168.9 2147.82
   211.7  2148.4   242.2 2149.83   256.9 2150.03   297.6 2151.46   309.2 2151.44
   318.5 2152.23   345.2 2155.16   369.7 2158.53   384.4    2161   428.5  2170.4
   441.7 2173.51   448.6 2175.47   462.8  2178.5   472.6 2180.28   489.7 2182.65
#Mann= 6 ,-1 , 0
       0     .05       0   25.73      .1       0  128.83     .05       0
  132.93      .1       0   141.8    .045       0  161.48      .1       0
Bank Sta=141.8,161.48
XS Rating Curve= 0 ,0
Exp/Cntr=0.3,0.1

Type RM Length L Ch R = 1 ,4532    ,264.1,269.5,249.8
XS GIS Cut Line= 4
2129089.83337322357607.8868412822128942.61122671357771.775621116
 2128955.1112017358098.1644040352129009.27776003358216.220270276
#Sta/Elev= 30
       0 2174.28     9.8 2173.74    25.4 2170.27    49.1 2165.93    73.7  2160.3
    98.2 2155.44   114.3 2153.15   131.9 2151.57   220.1 2148.99     253 2148.94
   279.3 2149.68   328.5 2149.44   335.1 2148.91   348.2 2146.73   390.5 2146.16
  400.532145.492   410.6 2144.49   413.9 2144.52  419.552145.882   430.3  2145.6
   476.3 2146.59     496 2148.67     504 2150.03   520.2 2153.38   541.9 2159.55
   580.4 2172.07   602.7 2179.97   617.5 2184.23   642.3 2189.46   676.8 2194.78
#Mann= 6 ,-1 , 0
       0      .1       0   21.63     .05       0  249.58      .1       0
  347.76     .05       0  400.53    .045       0  419.55     .05       0
Bank Sta=400.53,419.55
XS Rating Curve= 0 ,0
Exp/Cntr=0.3,0.1

Type RM Length L Ch R = 1 ,4262    ,404.8,431,411.1
XS GIS Cut Line= 3
2128535.66683063357788.4425825332128796.77785695358017.609118953
2129007.88898328358217.609047025
#Sta/Elev= 30
       0 2172.96    25.8 2164.36    38.9 2160.87      52 2158.36    85.5  2154.8
   113.1 2152.58   158.6  2150.1   206.4  2148.7   226.6 2147.25   243.1 2146.56
   266.9 2146.31     279 2145.71   292.8 2145.82  298.252145.065   305.2    2143
   308.7 2143.42   313.9 2144.75   317.22144.902   407.6 2145.57   423.9 2146.38
     443 2148.61   452.7 2150.85   476.4 2158.55     489 2163.35   496.8 2164.57
   503.7  2167.2   529.2 2174.73   570.3 2185.24   595.6 2189.44   638.2 2194.97
#Mann= 6 ,-1 , 0
       0      .1       0   15.01     .05       0  298.25    .045       0
   317.2     .05       0  508.15      .1       0   512.3     .05       0
Bank Sta=298.25,317.2
XS Rating Curve= 0 ,0
Exp/Cntr=0.3,0.1

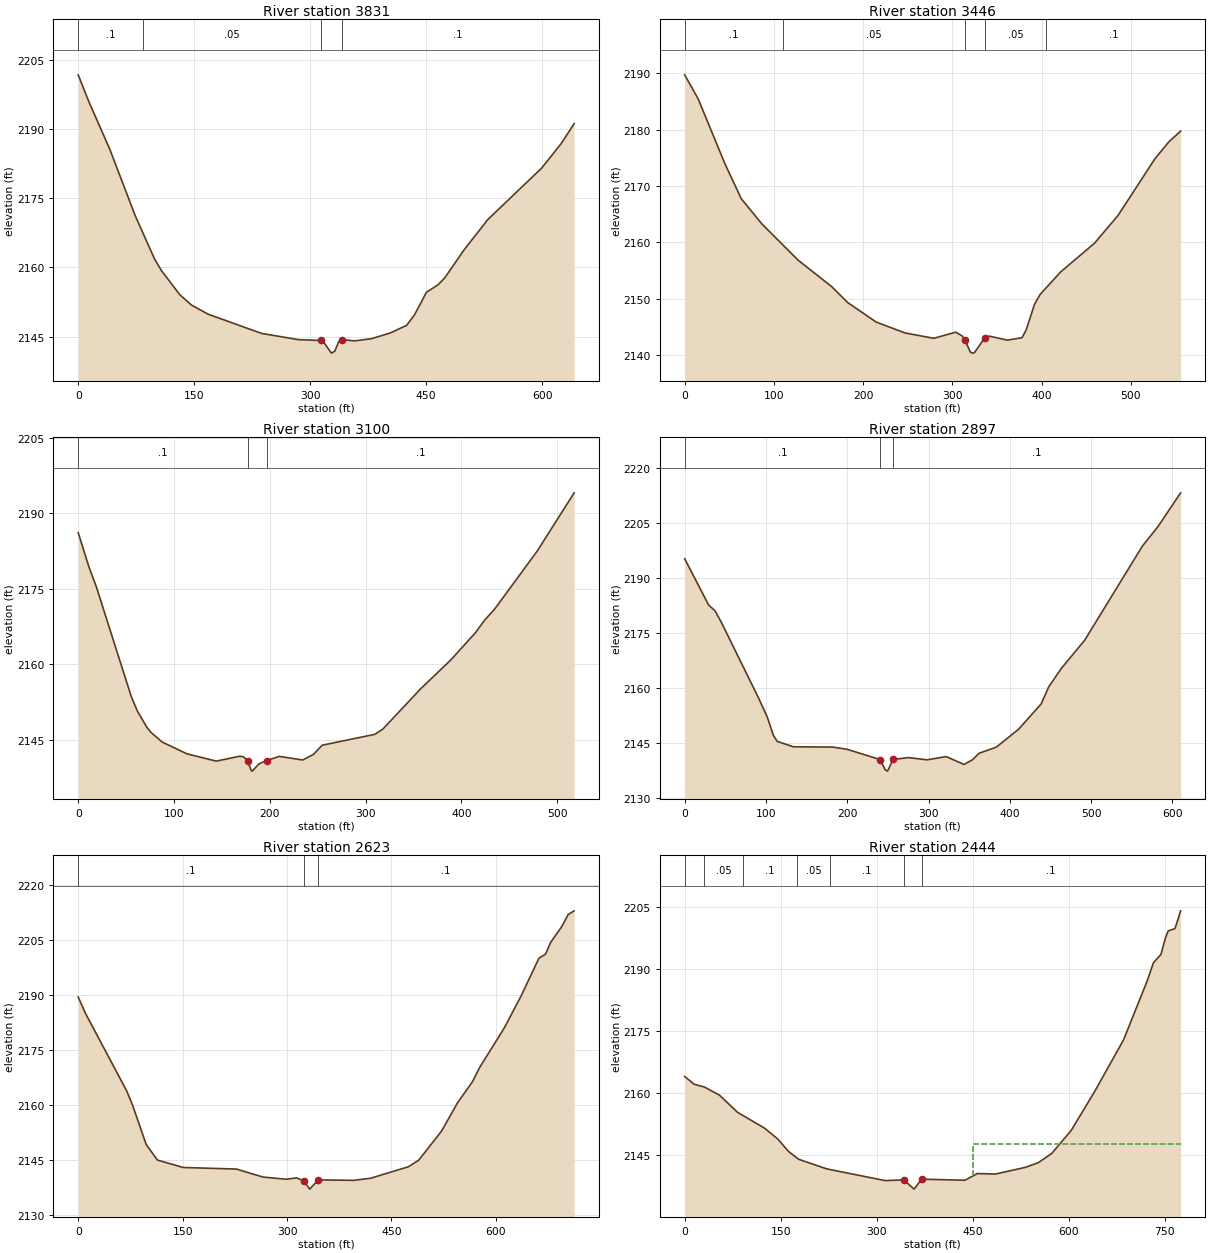
Type RM Length L Ch R = 1 ,3831    ,370.4,385.1,376
XS GIS Cut Line= 2
 2128354.6481638357986.5904801942128843.53694978358401.868521035
#Sta/Elev= 30
       0 2201.73    13.3  2196.1    40.9 2185.58    73.5  2171.3    98.7 2161.82
     108 2159.21   131.5 2154.05   146.7 2151.79   168.2 2149.83   237.1 2145.68
   284.5 2144.33  314.182144.143   317.9 2143.69   327.5  2141.4   331.9 2141.82
   336.9 2143.85     3412144.312   357.6 2144.06   379.2 2144.52     404 2145.79
   424.9 2147.43   435.1 2149.73   450.5 2154.61   465.3  2156.2   473.9 2157.66
   499.4 2163.85   529.8 2170.35   599.5 2181.52   624.5 2186.77   641.5 2191.15
#Mann= 4 ,-1 , 0
       0      .1       0   83.46     .05       0  314.18    .045       0
     341      .1       0
Bank Sta=314.18,341
XS Rating Curve= 0 ,0
Exp/Cntr=0.3,0.1

Type RM Length L Ch R = 1 ,3446    ,339,346.2,330.8
XS GIS Cut Line= 2
2128204.64813572358217.1461214422128601.87043837358606.035107449
#Sta/Elev= 30
       0 2189.72    15.1 2185.46      45 2173.99    63.4 2167.75    86.3 2163.32
   127.6 2156.79   164.8 2152.16   182.8 2149.32   214.9 2145.85     247 2143.94
   279.2 2142.99     304 2144.08   311.3 2143.38  313.922142.733   320.2 2140.56
   322.5 2140.36   324.8 2140.44  336.53 2143.12   341.1 2143.39   361.8 2142.66
   378.2  2143.1   382.8  2144.5   392.1 2149.01   398.5 2150.79   421.5 2154.77
   459.4 2159.86   485.8 2164.79   527.1 2174.83   542.9 2177.87   555.9 2179.73
#Mann= 5 ,-1 , 0
       0      .1       0  110.35     .05       0  313.92    .045       0
  336.53     .05       0  404.92      .1       0
Bank Sta=313.92,336.53
XS Rating Curve= 0 ,0
Exp/Cntr=0.3,0.1

Type RM Length L Ch R = 1 ,3100    ,202.5,203,201.1
XS GIS Cut Line= 2
2128067.14808261358504.6462026092128487.98155853358806.035035536
#Sta/Elev= 30
       0 2186.12    10.9 2179.47      19 2175.31    55.3  2153.6    61.8 2150.64
    71.5 2147.49    75.9 2146.44    87.7  2144.5   113.6 2142.16   144.1 2140.72
   168.3 2141.68   172.4 2141.59  176.912140.775   180.4  2138.9   181.7 2138.73
   188.5 2140.16  196.572140.837     210 2141.66   234.3 2140.94   245.6 2142.06
   254.6 2143.88   309.6 2146.04   318.1 2147.11   357.3 2155.07   388.7 2160.79
   414.5 2166.21   423.9 2168.67   434.7 2170.95   479.1 2182.47   517.6 2194.03
#Mann= 3 ,-1 , 0
       0      .1       0  176.91    .045       0  196.57      .1       0
Bank Sta=176.91,196.57
XS Rating Curve= 0 ,0
Exp/Cntr=0.3,0.1

Type RM Length L Ch R = 1 ,2897    ,265.4,274.1,274.6
XS GIS Cut Line= 3
2127886.59266946358635.2017157822128149.09247255358790.757178947
2128401.87051028358961.590498701
#Sta/Elev= 30
       0 2195.24    29.5 2182.62    37.2  2181.1    44.8 2178.06    90.6 2157.45
   101.6 2152.14     109  2147.2   113.8  2145.5   133.8 2144.02   182.1 2143.94
     200 2143.33  240.212140.556   246.9 2137.71   249.6 2137.39  256.442140.572
   275.4 2141.08   298.2 2140.46   321.8 2141.35   343.7 2139.21   354.2 2140.49
   362.1 2142.25   383.4 2143.91     411 2148.83   438.7 2155.72   447.9 2160.34
   463.7 2165.44   492.1 2173.02   562.9 2198.59   582.7 2204.11   610.2 2213.19
#Mann= 3 ,-1 , 0
       0      .1       0  240.21    .045       0  256.44      .1       0
Bank Sta=240.21,256.44
XS Rating Curve= 0 ,0
Exp/Cntr=0.3,0.1

Type RM Length L Ch R = 1 ,2623    ,179,179.3,172.8
XS GIS Cut Line= 3
2127733.81475979 358733.812739032127903.25930279358894.923965365
2128199.09270063 359271.31297636
#Sta/Elev= 30
       0 2189.42    10.5 2184.96    69.7 2163.85    78.4 2159.85    97.6 2149.32
   113.8 2145.05   150.9 2143.03   227.3  2142.6   265.6 2140.42     299 2139.83
   313.9  2140.2   324.22139.349   332.6 2137.14  344.792139.652   395.7 2139.53
     420  2140.1   474.3 2143.22   489.2 2145.02   521.9 2152.91   545.2 2160.71
   566.3 2166.34   577.1 2170.36     612 2180.97   636.4 2189.75   661.9 2199.98
   671.4 2201.08   678.7 2204.27   694.8 2208.62   703.8 2211.86   712.5 2212.88
#Mann= 3 ,-1 , 0
       0      .1       0   324.2    .045       0  344.79      .1       0
Bank Sta=324.2,344.79
XS Rating Curve= 0 ,0
Exp/Cntr=0.3,0.1

Type RM Length L Ch R = 1 ,2444    ,211.1,213.3,207.5
XS GIS Cut Line= 3
2127540.75937164358840.7574070252127765.75924972359012.979503527
2128153.25913087359315.757113203
#Sta/Elev= 30
       0 2164.08    14.7 2162.22    31.1 2161.52    54.4 2159.57    82.6 2155.42
   124.6 2151.61   145.3    2149   162.6 2145.91   178.3 2144.05     222 2141.74
   313.4  2138.9  342.362139.076   358.6 2136.84  370.232139.247   438.1 2138.99
   457.3 2140.61   485.6 2140.49   531.9 2142.08   552.6 2143.23   573.7 2145.47
   604.1 2151.05   639.7 2160.17   685.9 2172.93   723.3 2187.38   732.6 2191.59
   744.3 2193.59   751.3 2197.56   755.7 2199.29   766.3 2199.86   775.1 2204.15
#Mann= 7 ,-1 , 0
       0      .1       0   30.73     .05       0   91.75      .1       0
  175.42     .05       0  226.66      .1       0  342.36    .045       0
  370.23      .1       0
#XS Ineff= 2 , 0
                          451.39         2147.79
Permanent Ineff=
       F       F
Bank Sta=342.36,370.23
XS Rating Curve= 0 ,0
Exp/Cntr=0.3,0.1

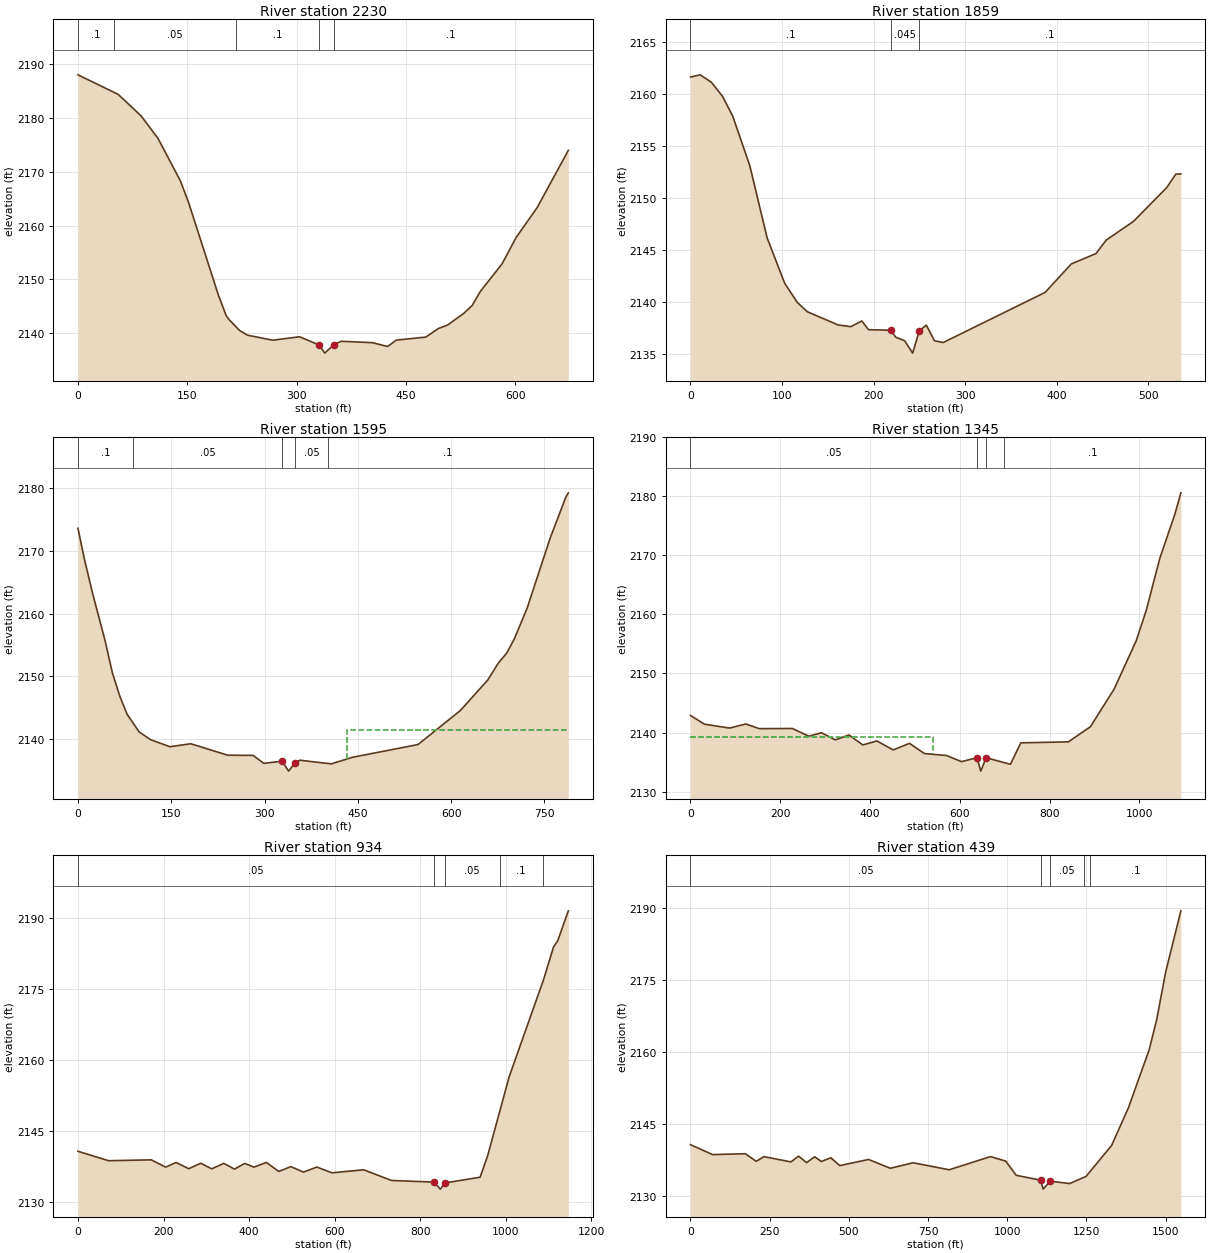
Type RM Length L Ch R = 1 ,2230    ,317.3,371.7,325.9
XS GIS Cut Line= 2
2127435.20380846  359056.03519172128024.09272254359381.035197869
#Sta/Elev= 30
       0    2188    55.2 2184.37    86.6 2180.38   109.9 2176.17   140.6 2168.28
   151.8 2164.27   192.4 2147.17   203.6 2143.18   207.3 2142.53   221.8  2140.5
   232.6 2139.63   267.3  2138.7   303.9 2139.34  331.032137.805   338.5  2136.3
  351.032137.868     361  2138.5   404.1 2138.24   424.7 2137.53   436.7 2138.71
   477.1 2139.28   494.6 2140.89   507.1 2141.52   529.6 2143.73   540.9 2145.19
   552.1  2147.8   581.6 2152.86     601 2157.78   629.9 2163.35   672.6 2173.97
#Mann= 5 ,-1 , 0
       0      .1       0   49.06     .05       0  216.61      .1       0
  331.03    .045       0  351.03      .1       0
Bank Sta=331.03,351.03
XS Rating Curve= 0 ,0
Exp/Cntr=0.3,0.1

Type RM Length L Ch R = 1 ,1859    ,243.4,263.8,254.9
XS GIS Cut Line= 2
2127372.42145371359333.6176417772127846.37982339359583.617469862
#Sta/Elev= 30
       0 2161.59    10.6  2161.8    22.8 2161.09    35.1 2159.72    46.2 2157.82
    64.8 2153.08    83.7 2146.15   102.9 2141.79   116.7 2139.94   127.8 2139.04
   161.2 2137.78   175.2 2137.61   187.2 2138.16   194.6 2137.32  218.912137.269
   224.3  2136.6     234 2136.26   242.8 2135.07  249.972137.215   257.7 2137.76
   266.6 2136.26   276.2 2136.09   387.5  2140.9   416.2 2143.64   443.1 2144.63
   454.3 2145.93   484.2 2147.73   520.6 2150.99   530.3 2152.26   535.9 2152.28
#Mann= 3 ,-1 , 0
       0      .1       0  218.91    .045       0  249.97      .1       0
Bank Sta=218.91,249.97
XS Rating Curve= 0 ,0
Exp/Cntr=0.3,0.1

Type RM Length L Ch R = 1 ,1595    ,250.3,249.7,239
XS GIS Cut Line= 4
2127164.08820897359456.5340626092127332.83819956359569.034165695
2127623.46327445359704.4508896172127879.71341813359772.159087539
#Sta/Elev= 30
       0 2173.62    10.4  2168.7    23.5 2163.26    43.6 2155.71    55.4 2150.56
    67.2 2146.87      79 2143.96    98.4 2141.14   116.9 2139.89   148.1 2138.77
   181.2 2139.25   240.9 2137.42   281.7 2137.39   298.8 2136.12  328.482136.466
   338.7 2134.88  349.132136.171   356.8 2136.62   407.4 2136.04   441.5 2137.09
   546.8 2139.12   614.9 2144.55     659 2149.42     676 2152.13   689.4  2153.7
   701.7 2155.98   722.1 2160.83   759.2 2172.02   784.6 2178.62   788.5 2179.27
#Mann= 5 ,-1 , 0
       0      .1       0   88.86     .05       0  328.48    .045       0
  349.13     .05       0  402.07      .1       0
#XS Ineff= 1 ,-1
  432.37  788.48 2141.43
Permanent Ineff=
       F
Bank Sta=328.48,349.13
XS Rating Curve= 0 ,0
Exp/Cntr=0.3,0.1

Type RM Length L Ch R = 1 ,1345    ,403.8,411.6,400.5
XS GIS Cut Line= 4
2126809.92159447359677.0201701972127191.86604053359817.298104867
2127612.69951645359765.3884317872127873.28954646359786.742391706
#Sta/Elev= 30
       0 2142.89    31.1 2141.41    87.1 2140.75   123.1 2141.44   153.5 2140.65
   226.9 2140.68   263.7 2139.37   291.8 2139.96   322.5 2138.75   353.2 2139.58
   383.8 2137.89   415.2 2138.57   451.5 2137.05   487.9 2138.16   520.9 2136.44
   570.5  2136.1   603.6 2135.07   638.32135.726   646.6 2133.46  658.482135.726
   712.7 2134.62   735.8 2138.25   841.7 2138.41   890.9 2140.98   943.6 2147.34
     993 2155.55  1015.1 2160.65  1045.6 2169.53  1078.6 2176.88  1092.4 2180.58
#Mann= 4 ,-1 , 0
       0     .05       0   638.3    .045       0  658.48     .05       0
  698.66      .1       0
#XS Ineff= 2 , 0
          540.58 2139.27
Permanent Ineff=
       F       F
Bank Sta=638.3,658.48
XS Rating Curve= 0 ,0
Exp/Cntr=0.3,0.1

Type RM Length L Ch R = 1 ,934     ,472.4,494.6,489.4
XS GIS Cut Line= 5
 2126824.6784547 359713.131318452127349.27353412360116.430052534
2127379.65536311360137.263344198 2127697.3637172360069.555146277
2127818.19713697360047.506305858
#Sta/Elev= 30
       0 2140.68    71.7 2138.68   171.4 2138.86   205.1 2137.32   229.3 2138.31
   258.9 2136.99     287 2138.15   312.7 2136.96   341.1 2138.12   365.9  2136.9
   389.9 2138.11   411.4 2137.32   440.4 2138.31   469.4 2136.41   497.5 2137.43
   527.3 2136.27   558.4 2137.34   593.5 2136.12   667.8 2136.76     733  2134.5
  831.552134.155     847 2132.67  857.722133.979     940 2135.19   957.7 2139.76
    1008 2156.46  1088.2 2176.95  1111.5 2183.86  1121.5 2185.22  1146.2 2191.53
#Mann= 5 ,-1 , 0
       0     .05       0  831.55    .045       0  857.72     .05       0
  985.37      .1       0 1086.71      .1       0
Bank Sta=831.55,857.72
XS Rating Curve= 0 ,0
Exp/Cntr=0.3,0.1

Type RM Length L Ch R = 1 ,439     ,309.8,325.6,297.4
XS GIS Cut Line= 5
2126815.41928688359718.3396413622127347.36376104360143.339775622
 2127505.6971058360376.6729703692127668.19710886360501.673048452
2127986.25257513360710.006293193
#Sta/Elev= 30
       0 2140.62    69.8 2138.55   173.2 2138.73   207.5 2137.14     232 2138.12
   317.2 2137.02   341.2 2138.23   366.4 2136.87   392.3 2138.09   412.9 2137.11
   443.3 2137.88   471.2 2136.25   562.3 2137.53   630.9 2135.69   702.6 2136.85
   816.6 2135.38   946.9 2138.13   995.2 2137.19  1028.4 2134.22 1104.962133.217
  1113.4 2131.34 1135.33    2133  1197.1  2132.5  1248.9 2134.01  1329.5 2140.47
  1382.7 2148.35    1448 2160.44  1471.7 2166.74  1500.1 2176.68  1548.1 2189.44
#Mann= 5 ,-1 , 0
       0     .05       0 1104.96    .045       0 1135.33     .05       0
 1242.92      .1       0 1262.36      .1       0
Bank Sta=1104.96,1135.33
XS Rating Curve= 0 ,0
Exp/Cntr=0.3,0.1

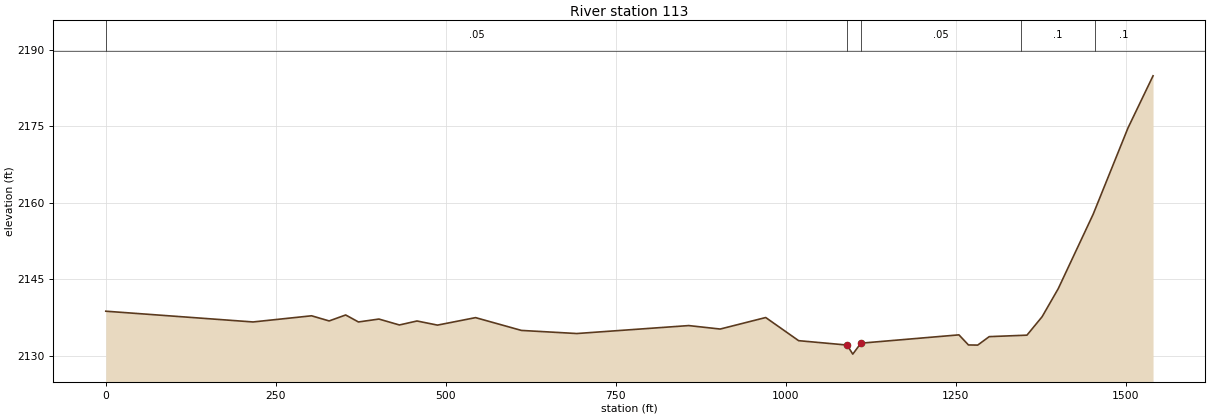
Type RM Length L Ch R = 1 ,113     ,110.64,113.49,116.35
XS GIS Cut Line= 5
2126815.41928688 359775.284081282127168.19712463360190.561794028
2127443.19723079360522.5063401162127551.53034747 360632.22856161
2127948.75265011  360732.2286897
#Sta/Elev= 30
       0  2138.7   216.5 2136.59   302.6  2137.8   328.4 2136.79   352.7 2137.96
   371.5 2136.59   401.6 2137.16   431.7    2136   457.6 2136.78   487.7 2135.97
   543.7 2137.44   611.1 2134.93   692.6 2134.32   857.1 2135.88   903.4  2135.2
   970.3 2137.46  1018.7 2132.92 1089.892132.061  1098.3 2130.28 1110.272132.427
  1254.4 2134.06  1268.4 2132.08    1282 2132.05  1298.9 2133.71  1354.4    2134
  1376.7 2137.62  1400.4 2143.12  1451.7  2157.7    1503 2174.66  1539.8 2184.87
#Mann= 5 ,-1 , 0
       0     .05       0 1089.89    .045       0 1110.27     .05       0
 1345.86      .1       0 1454.05      .1       0
Bank Sta=1089.89,1110.27
XS Rating Curve= 0 ,0
Exp/Cntr=0.3,0.1
LCMann Table=0

Chan Stop Cuts=-1
Use User Specified Reach Order=0
Composite Channel Slope=5